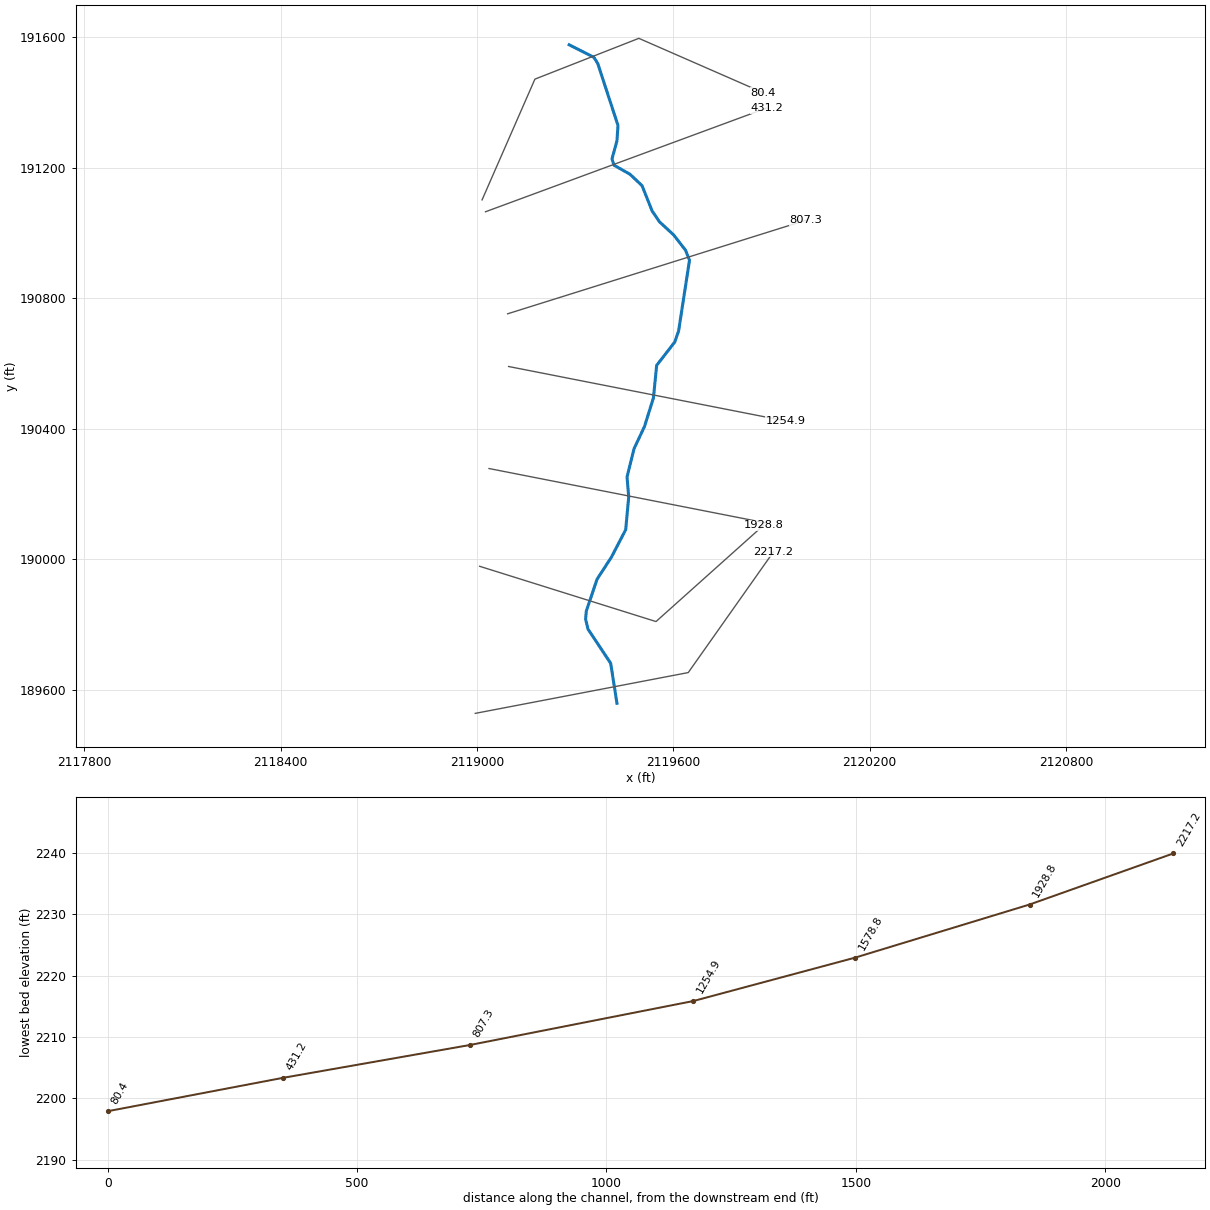
--- TRKYCKT1.prj (project) ---

Proj Title=TRKYCKT1
Current Plan=p01
Default Exp/Contr=0,0
English Units
Geom File=g01
Flow File=f01
Plan File=p01
BEGIN DESCRIPTION:
END DESCRIPTION:
DSS Export Rating Curves= 0
DSS Export Rating Curve Sorted= 0
DSS Export Volume Flow Curves= 0
DXF OffsetX= 0
DXF OffsetY= 0
DXF ScaleX= 0
DXF ScaleY= 0

--- TRKYCKT1.p01 (plan) ---

Plan Title=Floodplain
Program Version=4.00
Geom File=g01
Flow File=f01
K Sum by GR=0
Std Step Tol=0.01
Critical Tol=0.01
Num of Std Step Trials=20
Max Error Tol=0.3
Flow Tol Ratio=0.001
Split Flow NTrial=30
Split Flow Tol=0.02
Split Flow Ratio=0.02
Log Output Level=0
Friction Slope Method=1
Unsteady Friction Slope Method=2
Unsteady Bridges Friction Slope Method=1
Global Log Level=0
CheckData=False
Run HTab=0
Run UNet=0
Run PostProcess=0
UNET Theta=0
UNET Theta Warmup=0
UNET ZTol=0
UNET ZSATol=0
UNET MxIter=0
UNET MaxInSteps=0
UNET DtIC=0
UNET DtMin=0
UNET MaxCRTS=0
UNET WFStab=0
UNET SFStab=0
UNET WFX=0
UNET SFX=0
UNET DSS MLevel=0
UNET DZMax Abort=0
UNET Convert EG Bridges=0
UNET Use Existing IB Tables=0
UNET Froude Limit=0
UNET Froude Power=0
Write IC File=0
Echo Input=False
Echo Output=False
Write Detailed=0

--- TRKYCKT1.f01 (steady flow) ---

Flow Title=2010 USGS WV Regression Equation
Program Version=4.00
Number of Profiles=1
Profile Names=P100yr
River Rch & RM=TRKYCKT1,Main      ,2217.2
659.7897
River Rch & RM=TRKYCKT1,Main      ,80.4
675.1037
Boundary for River Rch & Prof#=TRKYCKT1,Main      ,1
Up Type=0
Dn Type=3
Dn Slope=0.01525

--- TRKYCKT1.g01 (geometry) ---

Geom Title=LiDAR
Program Version=4.10

River Reach=TRKYCKT1        ,Main
Reach XY= 30
     2119427.803      189559.218     2119408.635      189681.678
     2119339.419      189786.035     2119331.965      189816.916
     2119334.095      189841.407     2119367.105      189939.375
     2119410.765      190006.461     2119454.506      190090.749
     2119463.811       190191.31     2119458.684      190252.445
     2119479.981      190338.699     2119511.927       190406.85
     2119539.332      190494.696     2119549.197      190594.267
     2119604.399       190665.52     2119616.284      190699.688
     2119649.575      190916.137     2119637.423      190946.953
     2119601.376      190993.591     2119557.716      191034.055
     2119535.354      191067.066     2119504.473      191144.801
     2119467.203      191179.942     2119418.673      191207.369
     2119412.596      191226.467     2119427.803      191282.169
     2119430.997      191329.023     2119369.235      191518.568
     2119357.522      191537.736      2119281.75      191576.204

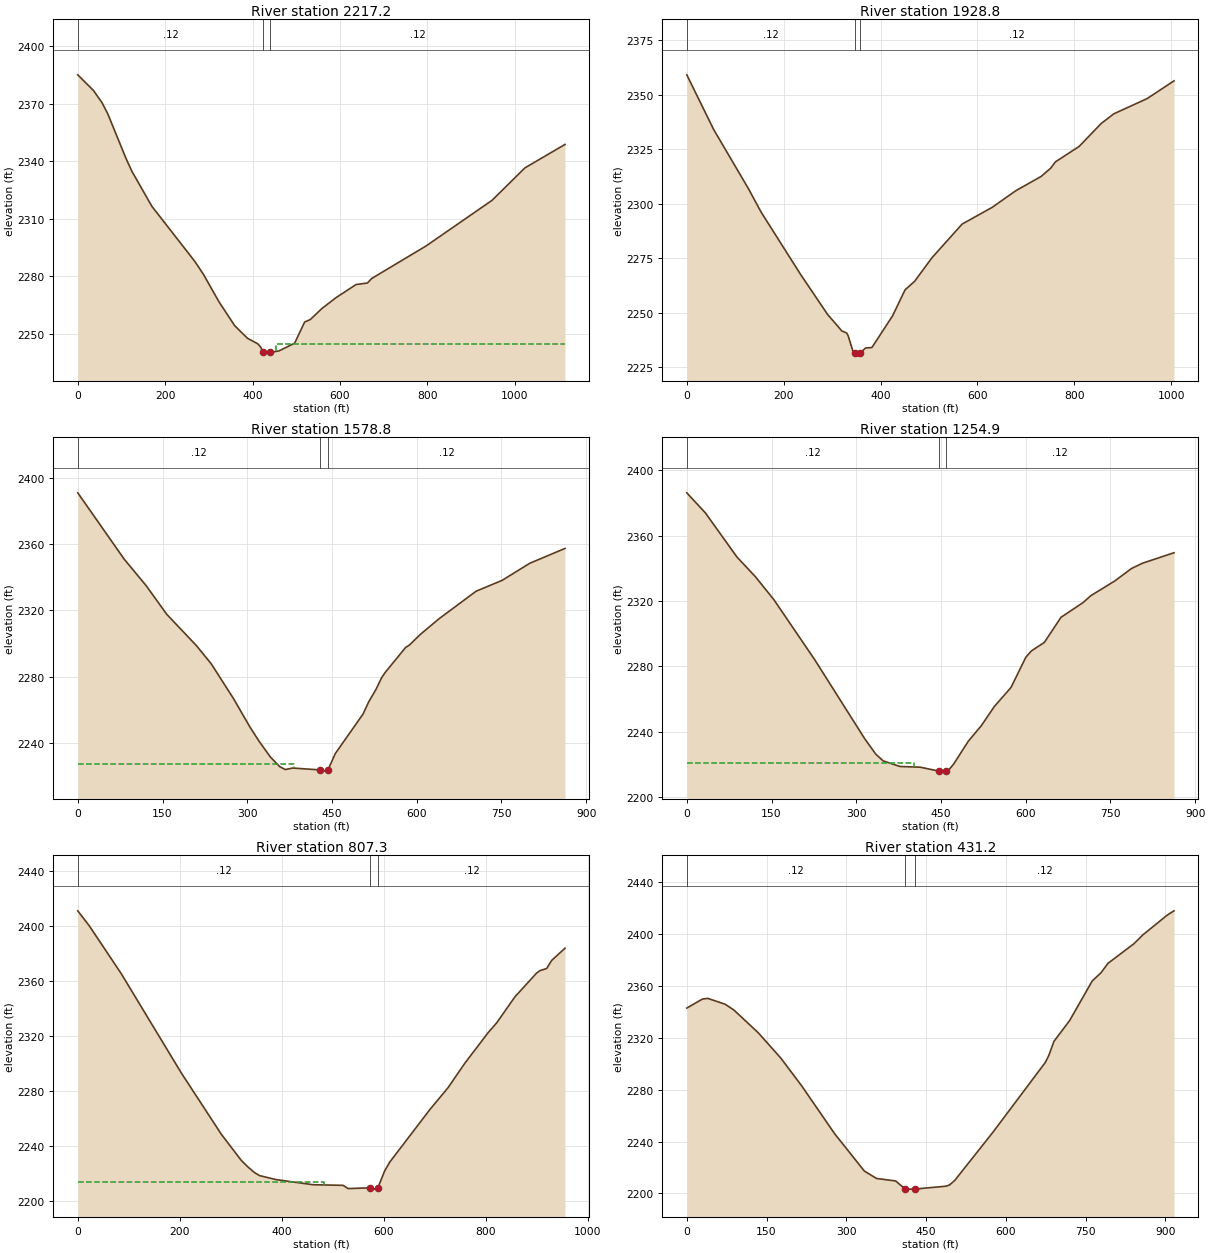
Type RM Length L Ch R = 1 ,2217.2  ,299.4,288.5,276.9
XS GIS Cut Line= 3
     2118994.709      189528.237     2119645.751      189653.237
     2119906.167      190023.029
#Sta/Elev= 30
       0 2385.19    35.9 2377.02    55.5 2370.66    68.6 2364.86     111 2341.22
   124.1 2334.74   169.8 2316.48   267.8 2287.84   287.4 2281.12   323.3 2266.67
   359.2 2254.22   388.6 2247.64   411.5 2244.84     418 2243.26   424.5 2240.31
   431.1 2239.91  440.222240.289   460.5 2241.07   496.4 2245.12   519.2 2256.14
   532.3 2257.45   558.4 2263.13   591.1 2268.87   636.8  2275.7   662.9 2276.51
   672.8 2278.88   797.3 2295.87   948.1 2319.66  1023.4  2336.6  1115.2 2348.86
#Mann= 3 ,-1 , 0
       0     .12       0   424.5    .045       0  440.22     .12       0
#XS Ineff= 2 , 0
                          453.79         2244.64
Permanent Ineff=
       F       F
Bank Sta=424.5,440.22
XS Rating Curve= 0 ,0
Exp/Cntr=0.3,0.1

Type RM Length L Ch R = 1 ,1928.8  ,346.8,350,352.5
XS GIS Cut Line= 3
      2119008.12      189978.758     2119547.183      189809.487
     2119875.308      190103.758
#Sta/Elev= 30
       0 2359.15    55.5 2334.06   127.4 2306.91   153.5 2296.18   235.2 2267.55
   290.7 2249.29   320.1 2241.74   329.9 2240.83   333.1 2239.54   342.9 2232.47
   346.2 2231.78   352.7 2231.58  358.232231.772   369.1 2233.94   382.1 2234.15
   424.6 2248.61   450.7 2260.63   470.3  2264.5   506.2 2275.33   568.3 2290.72
   630.3 2298.39   679.3 2306.04   731.5 2312.58   751.1 2316.34   760.9 2319.24
   809.9 2326.33   855.6 2336.88   881.7  2341.3   950.3 2348.26  1005.8  2356.4
#Mann= 3 ,-1 , 0
       0     .12       0   346.2    .045       0  358.23     .12       0
Bank Sta=346.2,358.23
XS Rating Curve= 0 ,0
Exp/Cntr=0.3,0.1

Type RM Length L Ch R = 1 ,1578.8  ,323.4,323.8,323.3
XS GIS Cut Line= 2
     2119036.766      190278.237      2119883.12       190111.57
#Sta/Elev= 30
       0 2390.91      82 2350.95   121.4 2334.74   157.4 2317.62   209.9 2298.73
   236.2 2287.73   275.5 2266.83     305 2249.43   321.4 2240.75   341.1 2231.41
   357.5 2225.63   367.4 2223.87   380.5 2224.78   429.7 2223.64   436.2 2222.92
  443.162223.789   455.9 2233.51   505.1 2257.41   514.9 2264.63   528.1 2272.34
   537.9 2279.28   544.5  2282.6   580.5  2297.6   587.1 2299.01   606.8 2305.55
   639.6 2314.91   705.2 2331.52   751.1 2338.04   800.3  2348.4   862.6 2357.35
#Mann= 3 ,-1 , 0
       0     .12       0   429.7    .045       0  443.16     .12       0
#XS Ineff= 2 , 0
           382.6 2227.01
Permanent Ineff=
       F       F
Bank Sta=429.7,443.16
XS Rating Curve= 0 ,0
Exp/Cntr=0.3,0.1

Type RM Length L Ch R = 1 ,1254.9  ,435.9,447.6,458.6
XS GIS Cut Line= 2
     2119096.662      190590.737     2119943.016       190424.07
#Sta/Elev= 30
       0 2386.15    32.8 2373.92    88.6 2346.96   121.4 2334.84   154.2 2320.76
   226.3 2284.13   314.9 2235.73   334.6 2226.24   347.7 2222.12   377.2 2218.71
   413.3 2218.27   446.1 2215.89   455.9 2215.86   459.2 2215.86   462.5 2216.04
   472.3 2220.11   498.5 2234.24   521.5 2243.69   544.5 2255.42     574 2267.06
   600.2 2285.52   610.1 2289.43     633 2294.63   662.5 2309.98   701.9 2319.07
     715 2323.15   757.6  2332.2   787.2 2339.82   806.8 2343.09   862.6 2349.49
#Mann= 3 ,-1 , 0
       0     .12       0   446.1    .045       0   459.2     .12       0
#XS Ineff= 2 , 0
          403.02 2220.66
Permanent Ineff=
       F       F
Bank Sta=446.1,459.2
XS Rating Curve= 0 ,0
Exp/Cntr=0.3,0.1

Type RM Length L Ch R = 1 ,807.3   ,374.3,376.1,375.4
XS GIS Cut Line= 2
     2119093.667      190752.195     2120005.126      191038.654
#Sta/Elev= 30
       0 2411.03    22.9 2399.96    85.1 2365.42   202.9 2293.23   281.4 2248.63
   320.6  2229.6   333.7  2224.8   346.8 2220.65   356.6 2218.52   389.4 2215.59
   461.4  2211.9   520.2 2211.45   530.1  2209.1   572.6 2209.64   579.1  2208.7
   585.7 2208.77  588.392209.653     602 2222.12   611.9 2228.44   690.4 2266.54
   726.4 2282.63   759.1 2300.31   804.9 2322.57   821.3 2329.52   857.2 2348.51
   899.8 2365.82   906.3 2367.56   919.4  2369.1   929.2 2374.97   955.4 2383.87
#Mann= 3 ,-1 , 0
       0     .12       0   572.6    .045       0  588.39     .12       0
#XS Ineff= 2 , 0
          482.37 2213.54
Permanent Ineff=
       F       F
Bank Sta=572.6,588.39
XS Rating Curve= 0 ,0
Exp/Cntr=0.3,0.1

Type RM Length L Ch R = 1 ,431.2   ,353,350.8,349.3
XS GIS Cut Line= 2
     2119025.959      191064.695     2119885.334      191382.404
#Sta/Elev= 30
       0 2342.92    29.4 2349.85    39.3 2350.41      72  2345.9    88.4 2341.47
   134.2 2323.95   176.7  2304.4     216 2282.97   278.1 2245.99   333.8 2217.31
   356.7 2211.56   392.7 2209.63  410.692203.414   412.3 2203.33   428.7 2203.38
   487.6  2205.6   494.1 2206.56   503.9 2210.08   575.9 2247.31   674.1 2300.97
   680.6 2306.26   690.4 2317.26   719.9  2333.3   762.4 2363.83   778.8  2370.1
   791.9 2377.38     841  2392.6   857.3 2399.24   903.1  2414.5   916.2 2417.89
#Mann= 3 ,-1 , 0
       0     .12       0  410.69    .045       0   428.7     .12       0
Bank Sta=410.69,428.7
XS Rating Curve= 0 ,0
Exp/Cntr=0.3,0.1

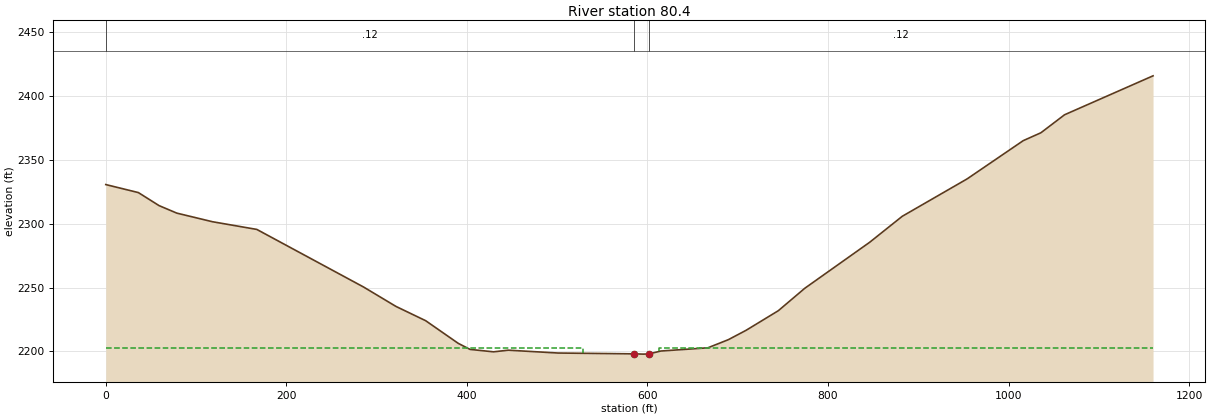
Type RM Length L Ch R = 1 ,80.4    ,66,80.4,93.2
XS GIS Cut Line= 4
     2119015.542      191101.154     2119177.001      191470.945
     2119494.709      191595.945     2119874.917      191429.279
#Sta/Elev= 30
       0 2330.76    36.1 2324.48      59 2314.27    78.7 2308.38   118.1 2301.65
   167.3 2295.61   285.4 2250.54   321.5 2235.25   354.3  2224.1   390.4 2206.35
   403.5  2201.6   429.5  2199.7   445.8 2200.99     501 2198.76   585.6 2198.12
   595.4  2197.9   601.8  2198.1   614.8 2200.33   666.9 2202.85   689.6 2209.23
   709.2 2216.55   744.9  2231.9   774.3 2249.52   846.2 2285.58   882.2 2305.89
   954.1 2335.22  1016.2 2365.16  1035.8 2371.35    1062 2385.45    1160 2415.96
#Mann= 3 ,-1 , 0
       0     .12       0   585.6    .045       0   601.8     .12       0
#XS Ineff= 2 , 0
          528.42 2202.38  613.25         2202.69
Permanent Ineff=
       F       F
Bank Sta=585.6,601.8
XS Rating Curve= 0 ,0
Exp/Cntr=0.3,0.1

Chan Stop Cuts=-1
Use User Specified Reach Order=0
Composite Channel Slope=5